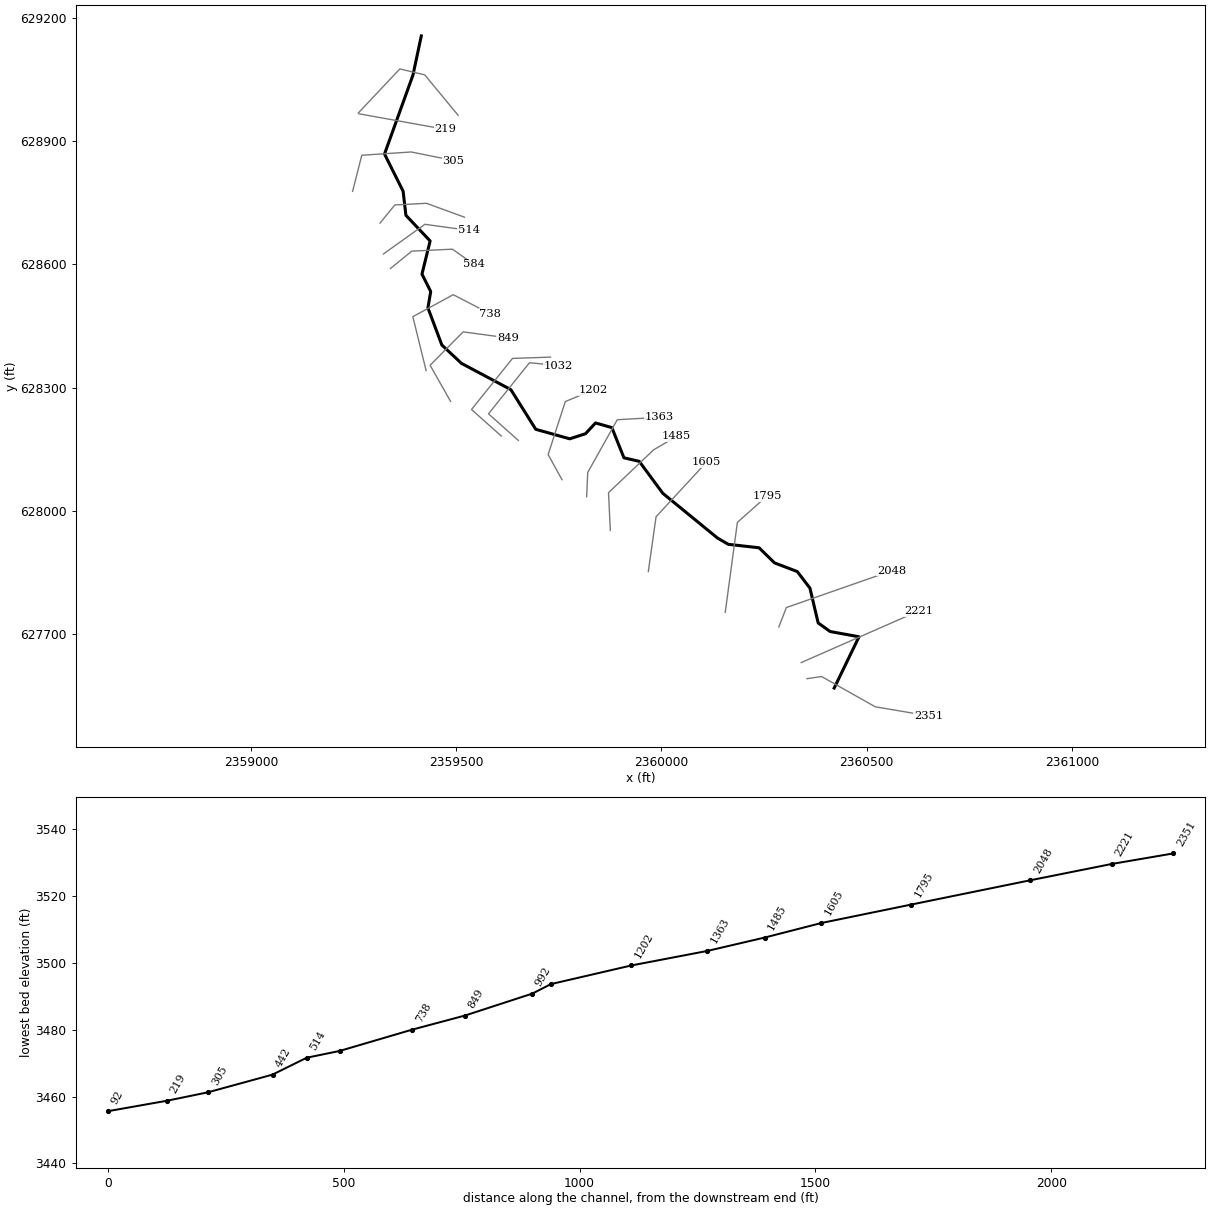
--- WARNERRN1.prj (project) ---

Proj Title=WARNERRN1
Current Plan=p01
Default Exp/Contr=0,0
English Units
Geom File=g01
Flow File=f01
Plan File=p01
BEGIN DESCRIPTION:
----------MODEL BY WOOD PLC 2022----------
AFH study
Randolph County, WV
HEC-RAS Version: RAS 6.2
Vertical Datum: NAVD88
Projection: NAD 1983 StatePlane West Virginia S FIPS 4702 (US Feet)
Terrain: 1-meter LIDAR (FEMA Region III 3DEP collected 2016-2018)
Land Use: 2019 NLCD
Hydrologic Method:
WV SIR2010-5033 regression equations
Additional Model Notes:
None
END DESCRIPTION:
DSS Export Rating Curves= 0
DSS Export Rating Curve Sorted= 0
DSS Export Volume Flow Curves= 0
DXF OffsetX= 0
DXF OffsetY= 0
DXF ScaleX= 0
DXF ScaleY= 0

--- WARNERRN1.p01 (plan) ---

Plan Title=Floodplain
Program Version=6.20
Short Identifier=Floodplain
Geom File=g01
Flow File=f01
Subcritical Flow
K Sum by GR= 0
Std Step Tol= 0.01
Critical Tol= 0.01
Num of Std Step Trials= 20
Max Error Tol= 0.3
Flow Tol Ratio= 0.001
Split Flow NTrial= 30
Split Flow Tol= 0.02
Split Flow Ratio= 0.02
Log Output Level= 0
Friction Slope Method= 1
Unsteady Friction Slope Method= 2
Unsteady Bridges Friction Slope Method= 1
Parabolic Critical Depth
Global Vel Dist= 0 , 0 , 0
Global Log Level= 0
CheckData=True
Encroach Param=-1 ,0,0, 0
Mapping Interval=1HOUR
Computation Time Step Use Courant=        0
Computation Time Step Use Time Series=    0
Computation Time Step Count To Double=0
Computation Time Step Max Doubling=0
Computation Time Step Max Halving=0
Computation Time Step Residence Courant=0
Run HTab= 0
Run UNet= 0
Run Sediment= 0
Run PostProcess= 0
Run WQNet= 0
Run RASMapper=-1
UNET Theta= 0
UNET Theta Warmup= 0
UNET ZTol= 0
UNET ZSATol= 0
UNET MxIter= 0
UNET Max Iter WO Improvement= 0
UNET MaxInSteps= 0
UNET DtIC= 0
UNET DtMin= 0
UNET MaxCRTS= 0
UNET WFStab= 0
UNET SFStab= 0
UNET WFX= 1
UNET SFX= 1
UNET Gravity=32.174
UNET 1D Methodology=Finite Difference
UNET DSS MLevel= 1
UNET Pardiso=0
UNET DZMax Abort= 0
UNET Use Existing IB Tables= 0
UNET Froude Reduction=False
UNET Froude Limit= 0
UNET Froude Power= 0
UNET D1 Cores= 0
UNET WindReference=Eulerian
UNET WindDragFormulation=Hsu (1988)
UNET D2 Coriolis=0
UNET D2 Cores= 0
UNET D2 Theta= 1
UNET D2 Theta Warmup= 1
UNET D2 Z Tol= 0.01
UNET D2 Volume Tol= 0.01
UNET D2 Max Iterations= 20
UNET D2 Equation= 0
UNET D2 RampUpFraction=0.1
UNET D2 TimeSlices= 1
UNET D2 Turbulence Formulation=Non-Conservative (original)
UNET D2 Eddy Viscosity=0.3
UNET D2 Transverse Eddy Viscosity=0.1
UNET D2 Smagorinsky Mixing=0
UNET D2 BCVolumeCheck=0
UNET D2 Cores=0
UNET D2 SolverType=PARDISO (Direct)
UNET D2 Minimum Iterations= 2147483647
UNET D2 Maximum Iterations= 2147483647
UNET D2 Restart Number= 10
UNET D2 Relaxation Coeff=1.3
UNET D2 SOR Precondition Iterations= 10
UNET D2 ILUT Maximum Fill= 8
UNET D2 ILUT Tolerance=1E-08
UNET D1D2 MaxIter= 0
UNET D1D2 ZTol=0.01
UNET D1D2 QTol=0.1
UNET D1D2 MinQTol=1
Write IC File= 0
Write IC File at Fixed DateTime=0
Write IC File at Sim End=0
Echo Input=False
Echo Parameters=False
Echo Output=False
Write Detailed= 0
HDF Write Warmup=0
HDF Write Time Slices=0
HDF Flush=0
HDF Compression= 1
HDF Chunk Size= 1
HDF Spatial Parts= 1
HDF Use Max Rows=0
HDF Fixed Rows= 1
Calibration Method= 0
Calibration Iterations= 20
Calibration Max Change=0.05
Calibration Tolerance=0.2
Calibration Maximum=1.5
Calibration Minimum=0.5
Calibration Optimization Method= 1
WQ AD Non Conservative
WQ ULTIMATE=-1
WQ Max Comp Step=1HOUR
WQ Output Interval=15MIN
WQ Output Selected Increments= 0
WQ Output face flow=0
WQ Output face velocity=0
WQ Output face area=0
WQ Output face dispersion=0
WQ Output cell volume=0
WQ Output cell surface area=0
WQ Output cell continuity=0
WQ Output cumulative cell continuity=0
WQ Output face conc=0
WQ Output face dconc_dx=0
WQ Output face courant=0
WQ Output face peclet=0
WQ Output face adv mass=0
WQ Output face disp mass=0
WQ Output cell mass=0
WQ Output cell source sink temp=0
WQ Output nsm pathways=0
WQ Output nsm derived pathways=0
WQ Create Restart=0
WQ Fixed Restart=0
WQ System Summary=0
WQ Write To DSS=0
Sorting and Armoring Iterations= 10
XS Update Threshold= 0.02
Bed Roughness Predictor= 0
Hydraulics Update Threshold= 0.02
Energy Slope Method= 1
Volume Change Method= 1
Sediment Retention Method= 0
Sediment TS Multiplier= 1
Warm Up Method= 0
XS Weighting Method= 0
Number of US Weighted Cross Sections= 1
Number of DS Weighted Cross Sections= 1
Upstream XS Weight=0
Main XS Weight=1
Downstream XS Weight=0
Number of DS XS's Weighted with US Boundary= 1
Upstream Boundary Weight= 1
Weight of XSs Associated with US Boundary= 0
Number of US XS's Weighted with DS Boundary= 1
Downstream Boundary Weight= 0.5
Weight of XSs Associated with DS Boundary= 0.5
Percentile Method= 0
Sediment Output Level= 3
Mass or Volume Output= 0
Output Increment Type= 1
Profile and TS Output Increment= 1
Transport Output Increment 1
XS Output Flag= 0
XS Output Increment= 10
Read HDF5 Sediment Hotstart= 0
Sediment Hotstart Type= 0
Write Gradation File= 0
Read Gradation Hotstart= 0
Write HDF5 File= 1
Write Binary Output= 1
Write DSS Sediment File= 0
DSS Sediment Output Type= 1
SV Curve= 0
Specific Gage Flag= 0
Subcell Erosion Methods= 0
Subcell Deposition Methods= 0
Advection Scheme= 1
Matrix Solver= 0
Implicit Weighting Factor= 1
Maximum Outer Loop Convergence Iterations= 5
Convergence Maximum Absolute= 0.001
Convergence RMSE= 0.0001
Grain Fractions Max Abs Error= 0.001
Max Subgrid Regions= 1
Max Subgrid Length Scale= 3.402823E+38
Initial Layer Thickness= 3.402823E+38
Min Layer Thickness= 3.402823E+38
Max Layer Thickness= 3.402823E+38
Number of Layers= 5

--- WARNERRN1.f01 (steady flow) ---

Flow Title=Flow
Program Version=6.20
Number of Profiles= 1
Profile Names=P100yr
River Rch & RM=WARNERRN1,Main,2351
     294
Boundary for River Rch & Prof#=WARNERRN1,Main            , 1
Up Type= 0
Dn Type= 3
Dn Slope=0.04327
DSS Import GetInterval= 0
DSS Import GetPeak= 0
DSS Import FillOption= 0

--- WARNERRN1.g01 (geometry) ---

Geom Title=Geometry
Program Version=6.20

River Reach=WARNERRN1       ,Main
Reach XY= 30
     2360420.609      627568.2862360481.08903707627693.178954463
2360410.69294849627705.9645381832360381.58430727627726.956230909
2360361.54330909627811.6649484852360330.77837954627851.957818048
2360275.31162986627873.128333193     2360237.716      627909.919
      2360162.78      627918.327     2360136.826      627933.314
     2360003.319      628042.504     2359945.843      628120.415
      2359908.57      628129.029     2359879.177       628202.59
     2359839.423       628213.92     2359815.063      628187.676
     2359776.599      628175.259     2359693.847      628198.428
     2359633.168      628295.086     2359513.031      628358.957
     2359465.114      628403.748     2359431.253       628494.19
     2359438.031      628533.957     2359416.764      628576.426
     2359436.605      628657.1382359377.64348667 628719.53412788
     2359370.843      628778.227     2359325.531      628868.853
     2359394.801       629061.04     2359415.097      629156.477

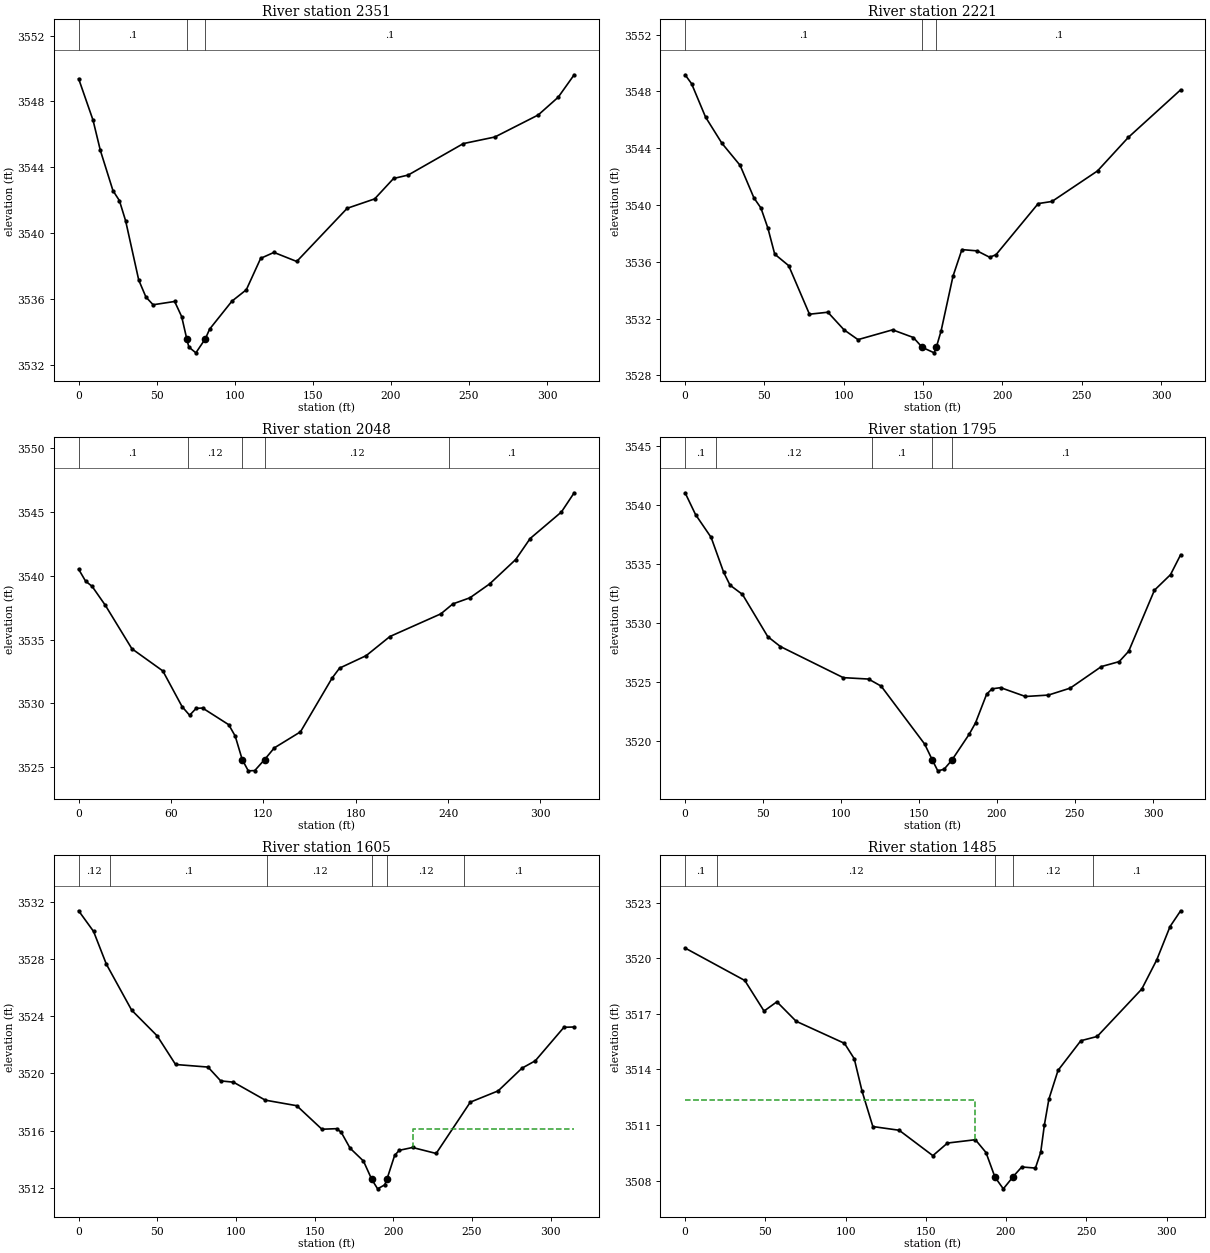
Type RM Length L Ch R = 1 ,2351    ,125.8,130.1,134
XS GIS Cut Line= 4
2360354.39569137627591.1323991792360389.94124767627596.359686869
2360520.62343992627522.6549304392360650.26017463627500.700322141
#Sta/Elev= 30
       0 3549.38     9.2 3546.87    13.9 3545.03      22 3542.58    26.1 3541.98
    30.1 3540.75    38.5 3537.15    43.1 3536.12    47.7 3535.65    61.5 3535.85
      66 3534.93   69.23 3533.59    70.6 3533.08    75.1 3532.73    81.23533.591
    83.9 3534.17    98.2 3535.87   107.4 3536.56   116.6 3538.47   125.1 3538.83
   139.7 3538.28     172 3541.51   189.6 3542.08   201.7 3543.32   211.1 3543.53
   246.4 3545.44   266.6 3545.84   294.4 3547.18   307.2 3548.26   317.4 3549.62
#Mann= 3 ,-1,0
       0      .1       0   69.23    .045       0    81.2      .1       0
Bank Sta=69.23,81.2
XS Rating Curve= 0 ,0
Exp/Cntr(USF)=0,0
Exp/Cntr=0.3,0.1

Type RM Length L Ch R = 1 ,2221    ,174.1,173.1,169.7
XS GIS Cut Line= 2
2360340.39931054627630.388691259 2360626.4670674627756.016976216
#Sta/Elev= 30
       0 3549.17     4.1 3548.54    12.9 3546.19    23.2 3544.35    34.7 3542.79
    43.4  3540.5    47.8 3539.79    52.2 3538.37    56.5 3536.54    65.3 3535.73
    78.4 3532.31      90 3532.45   100.2 3531.21     109 3530.52   130.8 3531.21
   143.9 3530.67  149.46 3529.98     157 3529.59  158.38 3529.98   161.4 3531.14
   168.9 3534.99   174.5 3536.86   184.1 3536.77     192 3536.32     196  3536.5
   222.6  3540.1   231.3 3540.25     260  3542.4   279.4 3544.76   312.4 3548.11
#Mann= 3 ,-1,0
       0      .1       0  149.46    .045       0  158.38      .1       0
Bank Sta=149.46,158.38
XS Rating Curve= 0 ,0
Exp/Cntr(USF)=0,0
Exp/Cntr=0.3,0.1

Type RM Length L Ch R = 1 ,2048    ,243.7,252.3,258.3
XS GIS Cut Line= 3
2360285.73276051627716.9535896672360304.15209218 627764.34527094
2360560.03105133627853.725436999
#Sta/Elev= 30
       0 3540.52     4.5 3539.59     8.8 3539.17    17.4 3537.68    34.6 3534.28
    54.7 3532.54    67.2 3529.74    72.1 3529.06    76.3  3529.6    80.5 3529.63
    97.5 3528.32   101.7 3527.43  106.273525.583   110.2  3524.7   114.4 3524.72
  120.793525.583   127.1  3526.5   144.1 3527.76   164.6 3531.97   169.5 3532.76
   186.8 3533.74   202.2 3535.24   235.3 3537.02   243.1  3537.8   254.2 3538.28
     267 3539.37   283.9 3541.28   293.3 3542.93   313.6 3545.01   321.9 3546.52
#Mann= 5 ,-1,0
       0      .1       0   70.85     .12       0  106.27    .045       0
  120.79     .12       0  240.85      .1       0
Bank Sta=106.27,120.79
XS Rating Curve= 0 ,0
Exp/Cntr(USF)=0,0
Exp/Cntr=0.3,0.1

Type RM Length L Ch R = 1 ,1795    ,194.3,190.6,186.8
XS GIS Cut Line= 3
2360155.27924114627752.6614787312360184.86546553627971.731770313
2360257.01128441628036.001661565
#Sta/Elev= 30
       0 3541.03     6.7 3539.18    16.7 3537.24    24.7 3534.29    28.8 3533.19
    36.8  3532.4      53 3528.82    61.1 3527.98   101.4 3525.34   117.6 3525.22
   125.7 3524.62   153.6  3519.7   158.53518.351     162 3517.43     166 3517.56
     1713518.331   182.2 3520.55   186.2  3521.5   193.3 3523.93   196.8 3524.39
   202.3 3524.49   218.2 3523.74   232.9 3523.86   246.9 3524.45   266.9 3526.28
   278.3  3526.7   284.4 3527.58   300.9 3532.76   311.2 3534.08   317.7 3535.77
#Mann= 5 ,-1,0
       0      .1       0      20     .12       0     120      .1       0
   158.5    .045       0     171      .1       0
Bank Sta=158.5,171
XS Rating Curve= 0 ,0
Exp/Cntr(USF)=0,0
Exp/Cntr=0.3,0.1

Type RM Length L Ch R = 1 ,1605    ,119.9,120.1,119.3
XS GIS Cut Line= 3
2359967.92548026627851.7877108332359986.81504076627985.363888657
2360108.92255685628117.590812161
#Sta/Elev= 30
       0 3531.41     9.5 3529.96    17.6 3527.67    33.7 3524.44    49.9 3522.64
    61.6 3520.63    82.2 3520.45    90.3 3519.48    98.4 3519.39   118.6 3518.13
   138.6 3517.74   154.6 3516.09     164 3516.13   166.9 3515.87   172.5 3514.76
     181 3513.86  186.28 3512.57     190 3511.91   194.5 3512.19   195.9 3512.58
   200.8 3514.25   203.7 3514.61   212.2 3514.81   227.2 3514.39   248.9 3517.99
   266.6 3518.78   281.7 3520.37   290.2 3520.89   308.4 3523.24   314.9 3523.26
#Mann= 6 ,-1,0
       0     .12       0      20      .1       0     120     .12       0
  186.28    .045       0   195.9     .12       0  244.91      .1       0
#XS Ineff= 2 , 0
                          212.28         3516.11
Permanent Ineff=
       F       F
Bank Sta=186.28,195.9
XS Rating Curve= 0 ,0
Exp/Cntr(USF)=0,0
Exp/Cntr=0.3,0.1

Type RM Length L Ch R = 1 ,1485    ,119.2,121.8,121.7
XS GIS Cut Line= 4
2359875.48090172627952.0353609152359870.99908191628044.087712292
 2359981.1176265628148.6073224342360037.04578358628181.316759529
#Sta/Elev= 30
       0 3520.55    37.2  3518.8    49.2 3517.15    57.2 3517.65    69.2  3516.6
    99.3 3515.41   105.4 3514.58   110.3 3512.82     117 3510.92   133.4 3510.72
   154.4 3509.35   163.5 3510.03   180.9 3510.21   187.5 3509.52   193.1 3508.19
   198.3 3507.56   204.1 3508.18   204.1 3508.19   209.8 3508.74   218.3 3508.68
   221.6 3509.53   223.9 3511.01   226.7  3512.4   232.4 3513.95   246.6 3515.55
   256.8 3515.78   284.6 3518.34   293.9 3519.91   302.2 3521.71   308.8 3522.56
#Mann= 5 ,-1,0
       0      .1       0      20     .12       0   193.1    .045       0
   204.1     .12       0  253.99      .1       0
#XS Ineff= 2 , 0
          180.41 3512.33
Permanent Ineff=
       F       F
Bank Sta=193.1,204.1
XS Rating Curve= 0 ,0
Exp/Cntr(USF)=0,0
Exp/Cntr=0.3,0.1

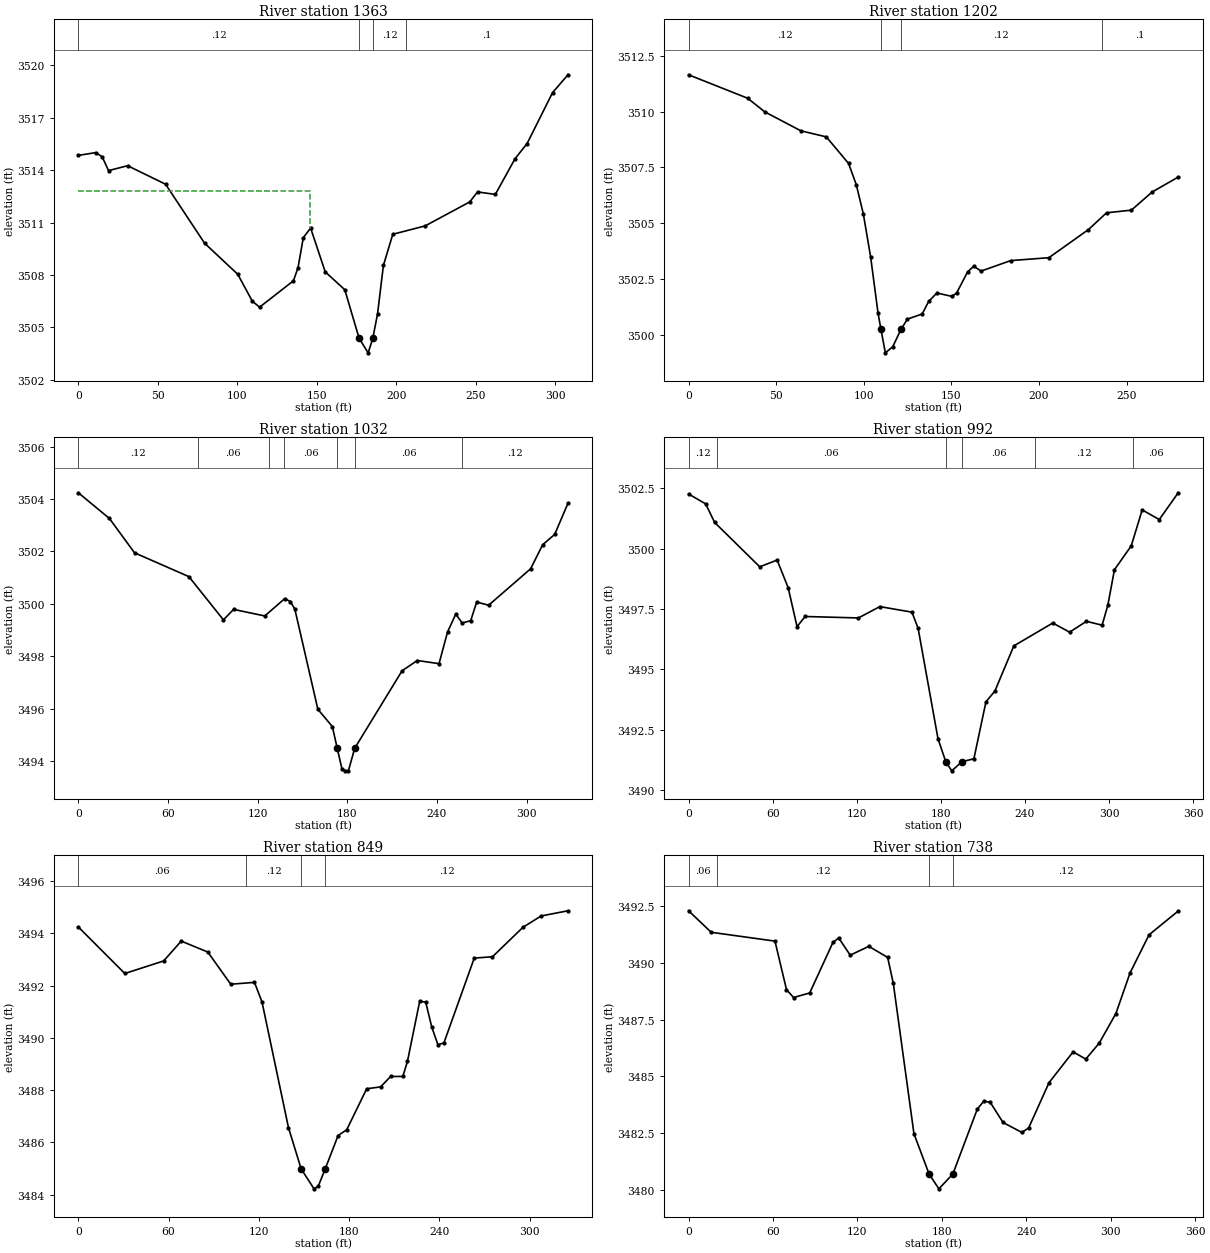
Type RM Length L Ch R = 1 ,1363    ,160.7,161.1,161.1
XS GIS Cut Line= 4
 2359817.7364184628034.2252104452359820.44323154628093.313831497
2359892.31718192628221.7335455432359993.80500063628227.532314735
#Sta/Elev= 30
       0 3514.84      11    3515      15 3514.76      19 3513.97      31 3514.25
    54.9 3513.19    79.4 3509.82   100.3 3508.04   109.4 3506.51     114 3506.16
   135.3 3507.67   138.2 3508.42   141.5 3510.13   146.1 3510.69   155.3 3508.18
   167.6 3507.16  176.62 3504.38   182.3 3503.55   185.2 3504.37   188.2 3505.77
   191.9 3508.55   197.8 3510.33   218.2 3510.81   246.2 3512.18   251.1 3512.75
   262.3 3512.61   274.7 3514.65   282.3 3515.52   298.3 3518.43     308 3519.45
#Mann= 4 ,-1,0
       0     .12       0  176.62    .045       0   185.2     .12       0
  206.32      .1       0
#XS Ineff= 2 , 0
          145.69  3512.8
Permanent Ineff=
       F       F
Bank Sta=176.62,185.2
XS Rating Curve= 0 ,0
Exp/Cntr(USF)=0,0
Exp/Cntr=0.3,0.1

Type RM Length L Ch R = 1 ,1202    ,174.3,170.3,170.3
XS GIS Cut Line= 4
2359757.76087249628075.6516257112359724.00670382628136.885858934
2359765.82500534628265.9998648792359833.97563086628294.287763731
#Sta/Elev= 30
       0 3511.65    33.7  3510.6    43.5 3509.99    64.1 3509.14    78.6 3508.87
    91.3 3507.68    95.7 3506.73    99.7 3505.43   103.9 3503.49   108.1 3500.99
  109.77 3500.25   112.3  3499.2   116.5 3499.47   121.23500.251   124.9 3500.71
   133.3 3500.94     137  3501.5   141.7 3501.88   150.1 3501.73   152.9 3501.87
   159.2 3502.82   162.7 3503.08   166.9 3502.86   183.8 3503.33   205.6 3503.46
   228.2 3504.72   238.5 3505.47   252.7 3505.59   264.5  3506.4   279.4 3507.07
#Mann= 4 ,-1,0
       0     .12       0  109.77    .045       0   121.2     .12       0
  235.64      .1       0
Bank Sta=109.77,121.2
XS Rating Curve= 0 ,0
Exp/Cntr(USF)=0,0
Exp/Cntr=0.3,0.1

Type RM Length L Ch R = 1 ,1032    ,39.6,39.3,39.6
XS GIS Cut Line= 4
2359651.43942142628171.3740550052359578.70634159628236.133407729
2359678.54753647628360.5428547522359749.03563344628353.780950926
#Sta/Elev= 30
       0 3504.24    20.8 3503.26    37.6 3501.95      74 3501.04    97.1 3499.39
   103.9 3499.79   124.8 3499.54   138.1  3500.2   141.9 3500.09   144.9  3499.8
   160.3 3495.98     170 3495.32  173.273494.491   176.4 3493.71   178.8 3493.63
   180.8 3493.64  184.953494.491   216.7 3497.45   226.9 3497.84   241.4 3497.72
   247.1 3498.93   252.6 3499.61   256.9 3499.27   262.6 3499.36   266.6 3500.07
   274.6 3499.95   302.7 3501.34   310.8 3502.26   318.8 3502.65   327.7 3503.84
#Mann= 7 ,-1,0
       0     .12       0      80     .06       0  127.39     .12       0
  137.39     .06       0  173.27    .045       0  184.95     .06       0
   256.9     .12       0
Bank Sta=173.27,184.95
XS Rating Curve= 0 ,0
Exp/Cntr(USF)=0,0
Exp/Cntr=0.3,0.1

Type RM Length L Ch R = 1 ,992     ,143.6,142.9,141.4
XS GIS Cut Line= 4
2359610.10370525628181.8749227882359537.37062542628246.634275511
 2359637.2118203628371.0437225342359729.65452557 628374.21366532
#Sta/Elev= 30
       0 3502.27    12.2 3501.86    18.6 3501.09    50.8 3499.25    63.2 3499.53
    71.1 3498.38    77.4 3496.77    83.2 3497.19   121.2 3497.13   136.5  3497.6
   159.4 3497.37   163.8  3496.7     178 3492.12  183.58 3491.16   187.8 3490.79
   195.1 3491.17   203.6 3491.29   212.2 3493.65   218.6  3494.1   232.1 3495.97
   259.9 3496.92   271.9 3496.54   283.9 3496.99   295.1 3496.83   299.2 3497.66
   303.9 3499.13   315.9 3500.12   323.7 3501.61   335.9 3501.21   349.4 3502.32
#Mann= 6 ,-1,0
       0     .12       0      20     .06       0  183.58    .045       0
   195.1     .06       0  247.39     .12       0   316.9     .06       0
Bank Sta=183.58,195.1
XS Rating Curve= 0 ,0
Exp/Cntr(USF)=0,0
Exp/Cntr=0.3,0.1

Type RM Length L Ch R = 1 ,849     ,112.9,111.2,108.2
XS GIS Cut Line= 4
2359486.47210541628266.2624629232359436.57794425628354.439526497
2359517.07515162628435.7018296652359625.91822901628421.061209862
#Sta/Elev= 30
       0 3494.24    30.9 3492.46    56.7 3492.94    68.4  3493.7    86.1 3493.28
   101.3 3492.05   117.1 3492.12   122.1 3491.37   139.7 3486.56  148.133484.981
   156.7 3484.22   159.5 3484.32  164.083484.981   172.7 3486.26   178.4 3486.48
   191.7 3488.05   200.9 3488.12   207.6 3488.52   215.7 3488.52   218.8  3489.1
   226.9 3491.39   230.9 3491.37   234.9 3490.42     239 3489.74     243  3489.8
   263.2 3493.05   275.3  3493.1   295.6 3494.23   307.6 3494.66   325.5 3494.86
#Mann= 4 ,-1,0
       0     .06       0  111.31     .12       0  148.13    .045       0
  164.08     .12       0
Bank Sta=148.13,164.08
XS Rating Curve= 0 ,0
Exp/Cntr(USF)=0,0
Exp/Cntr=0.3,0.1

Type RM Length L Ch R = 1 ,738     ,156.1,153.8,148
XS GIS Cut Line= 4
2359426.76645819628341.5623376642359394.52602618 628472.70985771
2359492.88666621628526.2617617292359582.50413824628479.813681713
#Sta/Elev= 30
       0 3492.31    16.1 3491.36    61.4 3490.97    69.6 3488.83    74.6 3488.48
    86.1 3488.68   102.6 3490.91   106.7 3491.11   114.9 3490.35   128.1 3490.74
   141.5 3490.25   145.5 3489.11   160.2 3482.46  170.963480.684   177.9 3480.03
  187.833480.683   205.2 3483.55   209.8  3483.9   214.4 3483.85   223.5 3482.96
   236.9 3482.52   241.7 3482.72   256.2 3484.72   273.3 3486.08   282.3 3485.76
   291.8 3486.46   303.7 3487.77   313.8 3489.57   327.3 3491.25     348  3492.3
#Mann= 4 ,-1,0
       0     .06       0      20     .12       0  170.96    .045       0
  187.83     .12       0
Bank Sta=170.96,187.83
XS Rating Curve= 0 ,0
Exp/Cntr(USF)=0,0
Exp/Cntr=0.3,0.1

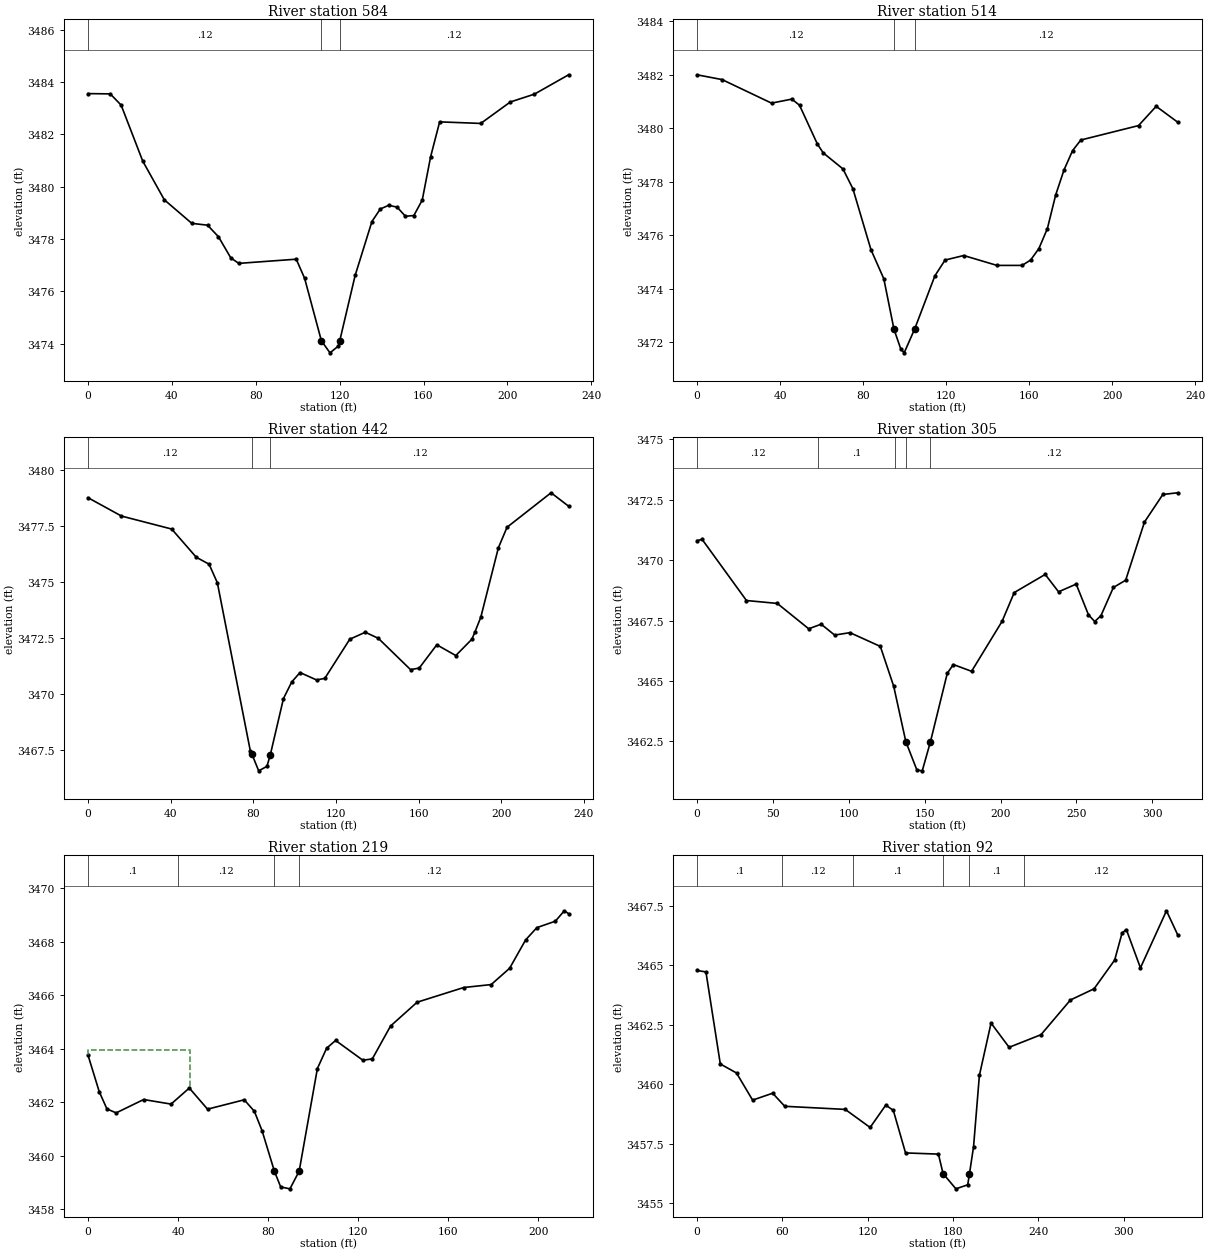
Type RM Length L Ch R = 1 ,584     ,68.3,70.4,72.4
XS GIS Cut Line= 4
2359339.90884735628589.977333631 2359392.1293082628632.351311518
2359490.89835397628637.1023102652359542.40298464 628600.68446075
#Sta/Elev= 30
       0 3483.56    10.6 3483.55    15.8 3483.12    26.1 3480.98    36.4  3479.5
    49.5  3478.6      57 3478.53    62.2 3478.09    68.1 3477.28    71.9 3477.07
    99.3 3477.23   103.3  3476.5   111.3 3474.11   115.4 3473.65   119.4 3473.91
  120.08 3474.12   127.4 3476.61   135.4 3478.67   139.4 3479.15   143.4 3479.29
   147.4 3479.22   151.4 3478.87   155.4  3478.9   159.4 3479.49   163.4 3481.15
   167.7 3482.48   187.3 3482.42   201.4 3483.24   212.9 3483.54   229.2 3484.28
#Mann= 3 ,-1,0
       0     .12       0   111.3    .045       0  120.08     .12       0
Bank Sta=111.3,120.08
XS Rating Curve= 0 ,0
Exp/Cntr(USF)=0,0
Exp/Cntr=0.3,0.1

Type RM Length L Ch R = 1 ,514     ,74.2,72.3,68.6
XS GIS Cut Line= 3
2359323.01743742628625.4606522822359423.79788931 628697.64331306
2359530.31543816628683.057399679
#Sta/Elev= 30
       0    3482    12.1 3481.82    35.9 3480.94    45.7 3481.09    49.4 3480.86
      58 3479.41    60.8 3479.08    70.3 3478.48    75.1 3477.74    83.8 3475.46
      90 3474.37    94.9 3472.48    98.1 3471.76    99.8  3471.6  104.85 3472.49
   114.6 3474.48   119.5 3475.07   128.5 3475.24   144.5 3474.87   156.6 3474.87
   160.7 3475.07   164.7  3475.5   168.8 3476.25   172.8 3477.51   176.8 3478.44
   180.9 3479.16   184.9 3479.56   212.7  3480.1   221.2 3480.82   231.5 3480.23
#Mann= 3 ,-1,0
       0     .12       0    94.9    .045       0  104.85     .12       0
Bank Sta=94.9,104.85
XS Rating Curve= 0 ,0
Exp/Cntr(USF)=0,0
Exp/Cntr=0.3,0.1

Type RM Length L Ch R = 1 ,442     ,137.5,136.3,134.7
XS GIS Cut Line= 4
 2359314.5769251628700.5910835632359350.63908661628744.767231407
2359427.72195683628748.8242245772359520.13124569628715.015948165
#Sta/Elev= 30
       0 3478.75    16.2 3477.93    40.5 3477.35    52.4 3476.09    58.6 3475.78
    62.6 3474.95    78.6 3467.42    79.4 3467.28    82.6 3466.55    86.6 3466.75
   88.24 3467.27    94.6 3469.78    98.6 3470.52   102.6 3470.94   110.6 3470.61
   114.6 3470.68   126.7 3472.43   134.2 3472.74   140.5 3472.47   156.1 3471.07
   160.3 3471.14   168.8 3472.18     178  3471.7   185.8 3472.43   187.3 3472.76
   190.1 3473.41   198.6 3476.51   202.8 3477.43   224.1 3478.97   232.6 3478.37
#Mann= 3 ,-1,0
       0     .12       0    79.4    .045       0   88.24     .12       0
Bank Sta=79.4,88.24
XS Rating Curve= 0 ,0
Exp/Cntr(USF)=0,0
Exp/Cntr=0.3,0.1

Type RM Length L Ch R = 1 ,305     ,89.2,86.6,84.3
XS GIS Cut Line= 4
2359247.80387497 628777.874244372359270.17766214628865.818016888
2359390.61437052628873.8157670542359493.65480949628853.005375056
#Sta/Elev= 30
       0 3470.81     3.4 3470.86    32.6 3468.33    52.9 3468.21    73.6 3467.16
    81.8 3467.35    90.7  3466.9   100.8    3467   120.8 3466.43   129.6 3464.78
  137.593462.488   144.9 3461.31   148.4 3461.28  153.823462.488   164.9 3465.32
   168.9 3465.68   180.9  3465.4     201 3467.47     209 3468.66   229.4 3469.41
   238.2 3468.69   249.8 3469.01   257.9 3467.74     262 3467.46   266.1  3467.7
   274.3 3468.87   282.4 3469.17   294.8 3471.58   306.9 3472.72   316.6 3472.79
#Mann= 5 ,-1,0
       0     .12       0      80      .1       0  130.75     .12       0
  137.59    .045       0  153.82     .12       0
Bank Sta=137.59,153.82
XS Rating Curve= 0 ,0
Exp/Cntr(USF)=0,0
Exp/Cntr=0.3,0.1

Type RM Length L Ch R = 1 ,219     ,125.9,126.5,126.6
XS GIS Cut Line= 2
2359263.89537112628966.7127452192359473.99993113 628928.80622797
#Sta/Elev= 30
       0 3463.76       5 3462.39     8.4 3461.75    12.5  3461.6    24.7  3462.1
    36.9 3461.93      45 3462.53    53.1 3461.74    69.4 3462.09    73.9 3461.66
    77.3 3460.94    82.8 3459.42    85.6 3458.83    89.7 3458.76    93.8 3459.42
   101.9 3463.26     106 3464.02     110 3464.31   122.1 3463.57   126.3 3463.62
   134.4 3464.85   146.2 3465.74   166.9 3466.29   179.1  3466.4   187.3 3467.01
   194.4 3468.07   199.4 3468.53   207.6 3468.77   211.6 3469.16   213.5 3469.05
#Mann= 4 ,-1,0
       0      .1       0      40     .12       0    82.8    .045       0
    93.8     .12       0
#XS Ineff= 2 , 0
           45.12 3463.95
Permanent Ineff=
       F       F
Bank Sta=82.8,93.8
XS Rating Curve= 0 ,0
Exp/Cntr(USF)=0,0
Exp/Cntr=0.3,0.1

Type RM Length L Ch R = 1 ,92      ,,,
XS GIS Cut Line= 4
2359261.53200088 628968.569637822359362.85747289629076.111800659
2359423.54628297629061.5276680032359504.81762372 628963.14710788
#Sta/Elev= 30
       0 3464.78     6.3 3464.72    16.4 3460.85    27.8 3460.47    39.1 3459.33
    53.2 3459.62    61.7 3459.07   104.2 3458.94   121.7 3458.18   132.7 3459.12
     138  3458.9   146.6 3457.11   169.7 3457.06  172.983456.241     182  3455.6
   190.3 3455.77  191.553456.241   194.4 3457.37   198.5 3460.37   206.7 3462.57
   219.4 3461.55   241.8 3462.08   262.5 3463.54   279.1 3464.01   293.6 3465.22
   298.8 3466.36   301.8  3466.5   311.7 3464.89     330 3467.29   337.8 3466.29
#Mann= 6 ,-1,0
       0      .1       0      60     .12       0     110      .1       0
  172.98    .045       0  191.55      .1       0  230.17     .12       0
Bank Sta=172.98,191.55
XS Rating Curve= 0 ,0
Exp/Cntr(USF)=0,0
Exp/Cntr=0.3,0.1
LCMann Table=0

Chan Stop Cuts=-1
Use User Specified Reach Order=0
Composite Channel Slope=5